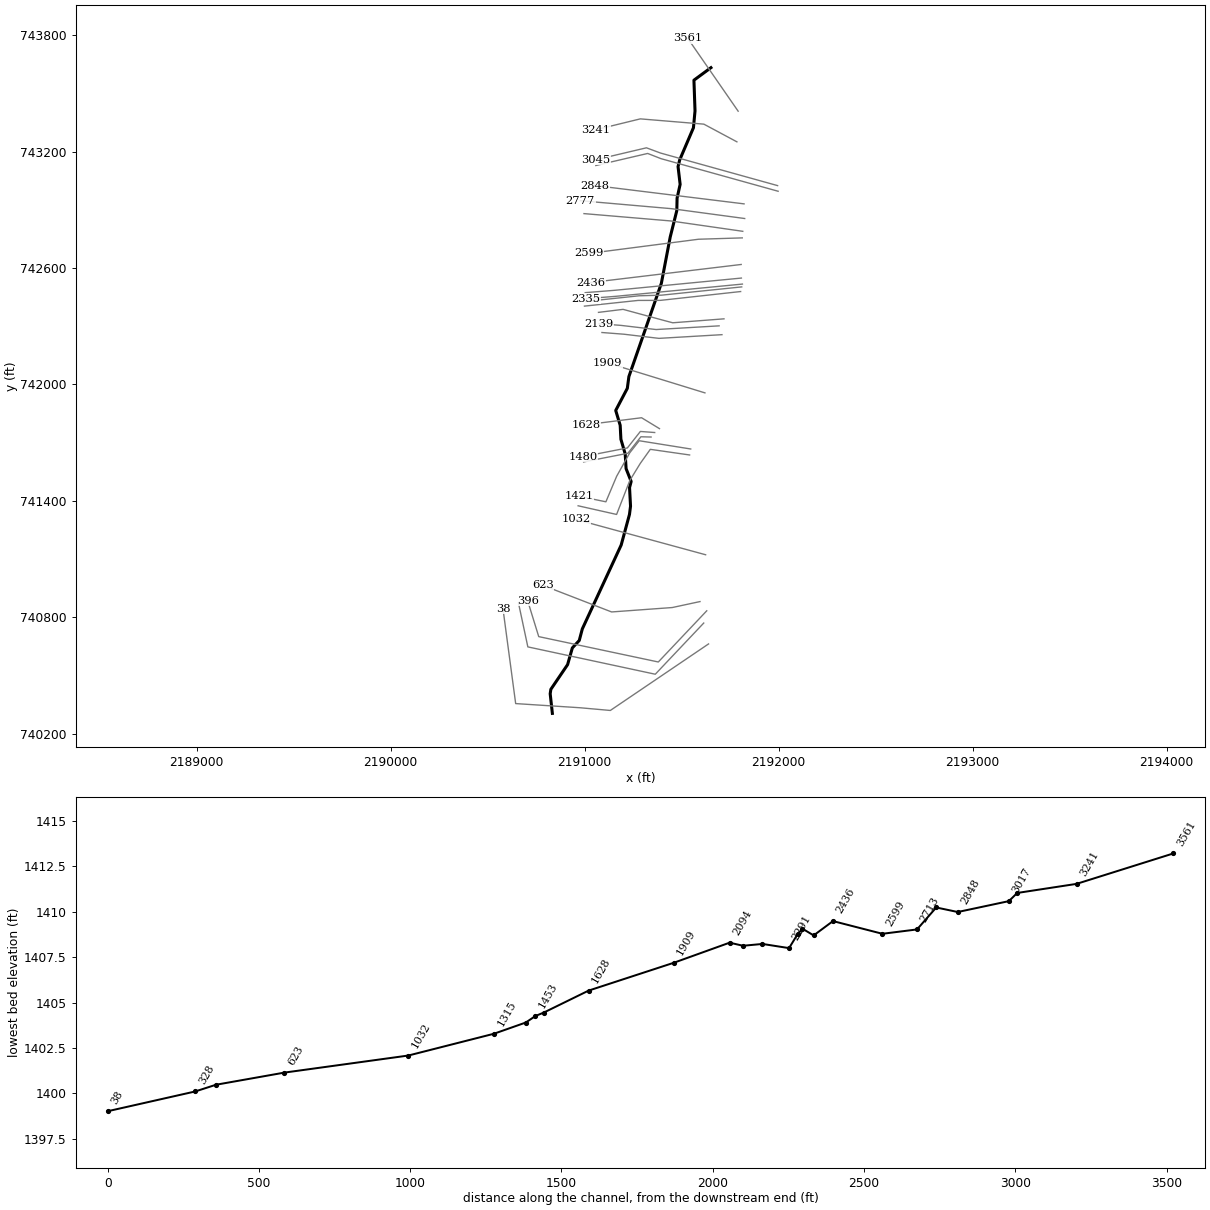
--- SUGARRN2.prj (project) ---

Proj Title=SUGARRN2
Current Plan=p01
Default Exp/Contr=0,0
English Units
Geom File=g01
Flow File=f01
Plan File=p01
BEGIN DESCRIPTION:
---------- MODELED AS PART OF WVEMD CTP PROGRAM, 2023----------
Stream Name: Sugar Run (II)
Flood Zone:  AFH
Upshur County, WV
HEC-RAS Version: RAS 6.3
Vertical Datum: NAVD88
Projection: NAD 1983 StatePlane West Virginia S FIPS 4702 (US Feet)
Terrain: 1-meter LIDAR (FEMA Region III 3DEP collected 2016-2018)
Land Use: 2019 NLCD
Hydrologic Method:
WV SIR2010-5033 regression equations
Additional Model Notes:
None
END DESCRIPTION:
DSS Export Rating Curves= 0
DSS Export Rating Curve Sorted= 0
DSS Export Volume Flow Curves= 0
DXF OffsetX= 0
DXF OffsetY= 0
DXF ScaleX= 0
DXF ScaleY= 0

--- SUGARRN2.p01 (plan) ---

Plan Title=Floodplain
Program Version=6.30
Short Identifier=Floodplain
Geom File=g01
Flow File=f01
Subcritical Flow
K Sum by GR= 0
Std Step Tol= 0.01
Critical Tol= 0.01
Num of Std Step Trials= 20
Max Error Tol= 0.3
Flow Tol Ratio= 0.001
Split Flow NTrial= 30
Split Flow Tol= 0.02
Split Flow Ratio= 0.02
Log Output Level= 0
Friction Slope Method= 1
Unsteady Friction Slope Method= 2
Unsteady Bridges Friction Slope Method= 1
Parabolic Critical Depth
Global Vel Dist= 0 , 0 , 0
Global Log Level= 0
CheckData=True
Encroach Param=-1 ,0,0, 0
Mapping Interval=1HOUR
Computation Time Step Use Courant=        0
Computation Time Step Use Time Series=    0
Computation Time Step Count To Double=0
Computation Time Step Max Doubling=0
Computation Time Step Max Halving=0
Computation Time Step Residence Courant=0
Run HTab= 0
Run UNet= 0
Run Sediment= 0
Run PostProcess= 0
Run WQNet= 0
Run RASMapper= 0
UNET Theta= 0
UNET Theta Warmup= 0
UNET ZTol= 0
UNET ZSATol= 0
UNET MxIter= 0
UNET Max Iter WO Improvement= 0
UNET MaxInSteps= 0
UNET DtIC= 0
UNET DtMin= 0
UNET MaxCRTS= 0
UNET WFStab= 0
UNET SFStab= 0
UNET WFX= 1
UNET SFX= 1
UNET Gravity=32.17405
UNET 1D Methodology=Finite Difference
UNET DSS MLevel= 1
UNET Pardiso=0
UNET DZMax Abort= 0
UNET Use Existing IB Tables= 0
UNET Froude Reduction=False
UNET Froude Limit= 0
UNET Froude Power= 0
UNET D1 Cores= 0
UNET WindReference=Eulerian
UNET WindDragFormulation=Hsu (1988)
UNET D2 Coriolis=0
UNET D2 Cores= 0
UNET D2 Theta= 1
UNET D2 Theta Warmup= 1
UNET D2 Z Tol= 0.01
UNET D2 Volume Tol= 0.01
UNET D2 Max Iterations= 20
UNET D2 Equation= 0
UNET D2 RampUpFraction=0.1
UNET D2 TimeSlices= 1
UNET D2 Turbulence Formulation=Non-Conservative (original)
UNET D2 Eddy Viscosity=0.3
UNET D2 Transverse Eddy Viscosity=0.1
UNET D2 Smagorinsky Mixing=0
UNET D2 BCVolumeCheck=0
UNET D2 Cores=0
UNET D2 SolverType=PARDISO (Direct)
UNET D2 Minimum Iterations= 3
UNET D2 Maximum Iterations= 30
UNET D2 Restart Number= 10
UNET D2 Relaxation Coeff=1.3
UNET D2 SOR Precondition Iterations= 10
UNET D2 ILUT Maximum Fill= 8
UNET D2 ILUT Tolerance=1E-08
UNET D2 Convergence Tolerance=0.00001
UNET D1D2 MaxIter= 0
UNET D1D2 ZTol=0.01
UNET D1D2 QTol=0.1
UNET D1D2 MinQTol=1
Write IC File= 0
Write IC File at Fixed DateTime=0
Write IC File at Sim End=0
Echo Input=False
Echo Parameters=False
Echo Output=False
Write Detailed= 0
HDF Write Warmup=0
HDF Write Time Slices=0
HDF Flush=0
HDF Compression= 1
HDF Chunk Size= 1
HDF Spatial Parts= 1
HDF Use Max Rows=0
HDF Fixed Rows= 1
Calibration Method= 0
Calibration Iterations= 20
Calibration Max Change=0.05
Calibration Tolerance=0.2
Calibration Maximum=1.5
Calibration Minimum=0.5
Calibration Optimization Method= 1
WQ AD Non Conservative
WQ ULTIMATE=-1
WQ Max Comp Step=1HOUR
WQ Output Interval=15MIN
WQ Output Selected Increments= 0
WQ Output face flow=0
WQ Output face velocity=0
WQ Output face area=0
WQ Output face dispersion=0
WQ Output cell volume=0
WQ Output cell surface area=0
WQ Output cell continuity=0
WQ Output cumulative cell continuity=0
WQ Output face conc=0
WQ Output face dconc_dx=0
WQ Output face courant=0
WQ Output face peclet=0
WQ Output face adv mass=0
WQ Output face disp mass=0
WQ Output cell mass=0
WQ Output cell source sink temp=0
WQ Output nsm pathways=0
WQ Output nsm derived pathways=0
WQ Create Restart=0
WQ Fixed Restart=0
WQ System Summary=0
WQ Write To DSS=0
Sorting and Armoring Iterations= 10
XS Update Threshold= 0.02
Bed Roughness Predictor= 0
Hydraulics Update Threshold= 0.02
Energy Slope Method= 1
Volume Change Method= 1
Sediment Retention Method= 0
Sediment TS Multiplier= 1
Warm Up Method= 0
XS Weighting Method= 0
Number of US Weighted Cross Sections= 1
Number of DS Weighted Cross Sections= 1
Upstream XS Weight=0
Main XS Weight=1
Downstream XS Weight=0
Number of DS XS's Weighted with US Boundary= 1
Upstream Boundary Weight= 1
Weight of XSs Associated with US Boundary= 0
Number of US XS's Weighted with DS Boundary= 1
Downstream Boundary Weight= 0.5
Weight of XSs Associated with DS Boundary= 0.5
Percentile Method= 0
Sediment Output Level= 3
Mass or Volume Output= 0
Output Increment Type= 1
Profile and TS Output Increment= 1
Transport Output Increment 1
XS Output Flag= 0
XS Output Increment= 10
Read HDF5 Sediment Hotstart= 0
Sediment Hotstart Type= 0
Write Gradation File= 0
Read Gradation Hotstart= 0
Write HDF5 File= 1
Write Binary Output= 1
Write DSS Sediment File= 0
DSS Sediment Output Type= 1
SV Curve= 0
Specific Gage Flag= 0
Subcell Erosion Methods= 0
Subcell Deposition Methods= 0
Advection Scheme= 1
Matrix Solver= 0
Implicit Weighting Factor= 1
Maximum Outer Loop Convergence Iterations= 5
Convergence Maximum Absolute= 0.001
Convergence RMSE= 0.0001
Grain Fractions Max Abs Error= 0.001
Max Subgrid Regions= 1
Max Subgrid Length Scale= 3.402823E+38
Initial Layer Thickness= 3.402823E+38
Min Layer Thickness= 3.402823E+38
Max Layer Thickness= 3.402823E+38
Number of Layers= 5

--- SUGARRN2.f01 (steady flow) ---

Flow Title=Flows
Program Version=6.31
Number of Profiles= 1
Profile Names=01pct
River Rch & RM=SUGARRN2,Main,3561
     446
Boundary for River Rch & Prof#=SUGARRN2,Main            , 1
Up Type= 0
Dn Type= 3
Dn Slope=0.00514
DSS Import GetInterval= 0
DSS Import GetPeak= 0
DSS Import FillOption= 0

--- SUGARRN2.g01 (geometry) ---

Geom Title=Geometry
Program Version=6.30

River Reach=SUGARRN2        ,Main
Reach XY= 30
 2191651.3390092743632.6933086282191563.66607313 743568.17544789
 2191569.2507419743409.5639064982191561.13343018 743323.01167342
2191490.21942771743157.1235604932191481.77565543743122.589048075
     2191492.542      743031.088     2191476.831       742960.09
     2191475.343      742895.789     2191441.375      742759.604
     2191395.675      742520.857     2191228.326      742040.245
     2191220.257      741979.607     2191160.391      741865.599
     2191183.485      741788.965     2191187.176      741716.966
     2191209.297      741641.562     2191213.904      741565.528
     2191240.002      741499.481     2191231.732      741467.889
     2191236.797      741372.053     2191231.331      741329.386
     2191188.578      741171.681     2190988.264       740739.43
     2190972.467      740679.736      2190936.84      740641.419
     2190912.316      740555.169     2190826.037      740427.941
     2190822.603      740405.076      2190833.85      740303.917

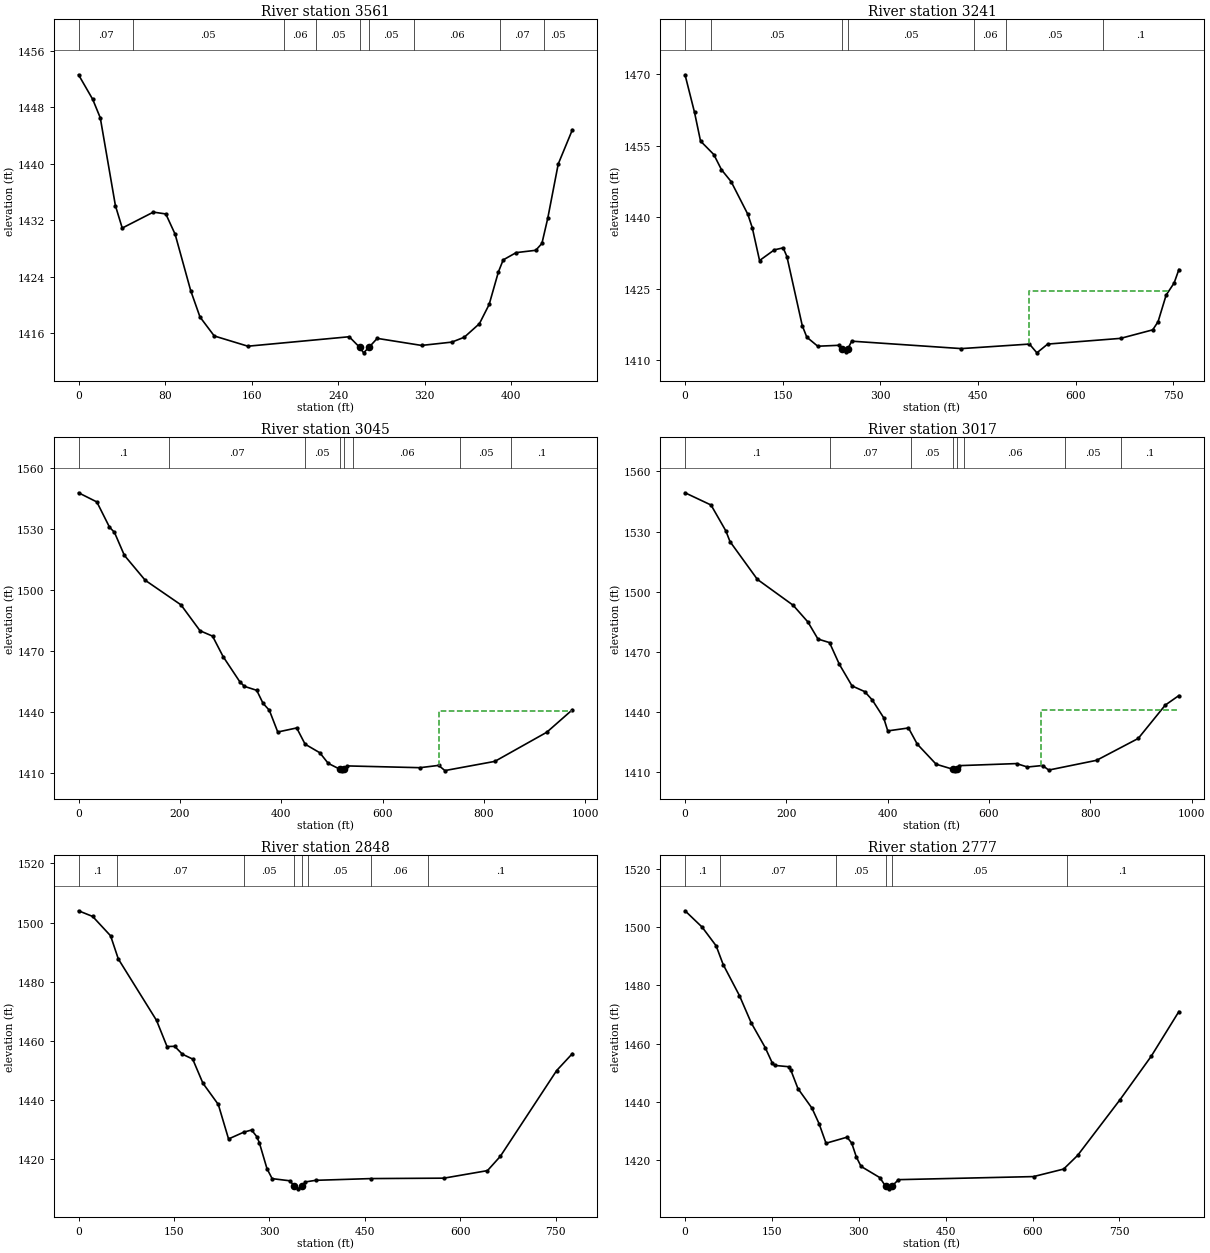
Type RM Length L Ch R = 1 ,3561    ,321.5,320.4,321.5
XS GIS Cut Line= 2
2191791.60290854743408.3676691142191531.74944198743783.929471722
#Sta/Elev= 30
       0 1452.62    13.1 1449.14    20.1 1446.52    34.1 1434.07    40.4  1430.9
    69.2 1433.16    80.7  1432.9    89.3 1430.03   103.7 1422.04   112.3  1418.3
   125.5 1415.61   156.6 1414.16   250.3  1415.5  260.081413.985   263.6 1413.22
   268.5 1413.99   276.2 1415.27   317.2 1414.27   345.2 1414.74   356.7 1415.43
   370.7 1417.35   379.7 1420.07   388.3  1424.7   392.7 1426.39   404.7 1427.42
   422.8 1427.75   428.5 1428.72   433.9 1432.28   443.6 1439.98   456.7 1444.84
#Mann= 9 ,-1,0
       0     .07       0      50     .05       0     190     .06       0
     220     .05       0  260.08    .045       0   268.5     .05       0
     310     .06       0     390     .07       0     430     .05       0
Bank Sta=260.08,268.5
XS Rating Curve= 0 ,0
Exp/Cntr(USF)=0,0
Exp/Cntr=0.3,0.1

Type RM Length L Ch R = 1 ,3241    ,197.4,196,194
XS GIS Cut Line= 4
2191785.15612019743250.3947738552191614.77657503743341.562776086
2191287.26433629743368.7526405392191057.14581465743312.546280543
#Sta/Elev= 30
       0 1469.94    14.6 1462.03    23.8 1456.02    44.2 1453.19      56    1450
    70.8 1447.51    96.4 1440.66   103.3 1437.82   114.5 1430.93   137.2 1433.17
   150.8 1433.59   156.5 1431.77   180.1 1417.26   187.1 1414.83   203.9 1412.93
     236 1413.12241.91241412.287   247.2 1411.66250.08111412.387   256.1 1413.99
   424.6 1412.43   529.2 1413.38   540.6 1411.54   557.2 1413.38   669.2 1414.58
   718.6 1416.37   726.8 1418.08   739.2 1423.67   751.5 1426.22   758.8 1429.04
#Mann= 7 ,-1,0
       0     .07       0      40     .05       0241.9124    .045       0
250.0811     .05       0  443.24     .06       0  493.24     .05       0
  641.88      .1       0
#XS Ineff= 1 ,-1
  527.97   744.4 1424.48
Permanent Ineff=
       F
Bank Sta=241.9124,250.0811
XS Rating Curve= 0 ,0
Exp/Cntr(USF)=0,0
Exp/Cntr=0.3,0.1

Type RM Length L Ch R = 1 ,3045    ,27.5,27.5,27.4
XS GIS Cut Line= 6
2191994.97771434743024.6612852442191632.19694383743125.603996747
2191559.94151091743145.7086153262191391.34637567743192.619938829
2191318.87442252743219.5533461532191055.22854609743157.366941153
#Sta/Elev= 30
       0  1547.7    36.1  1543.2      61 1530.85    70.9 1528.23    90.4 1516.97
   131.6  1504.7   202.2 1492.61   239.8 1479.89   264.5 1477.25   285.3 1467.21
   318.5 1454.75   327.5 1452.55   351.7 1450.61   364.1 1444.24   376.6 1440.81
   393.2 1430.12   430.6 1432.12   447.2 1424.14   476.2 1419.93   492.8 1414.72
  515.441411.881   519.2 1411.04   524.2  1411.9   530.2 1413.46   674.1 1412.59
   710.8 1413.72   723.1 1411.17   821.7 1415.69   924.2 1430.01   974.8 1441.07
#Mann= 8 ,-1,0
       0      .1       0  178.44     .07       0  446.56     .05       0
  515.44    .045       0   524.2     .05       0  541.56     .06       0
  753.88     .05       0  853.88      .1       0
#XS Ineff= 2 , 0
                          712.44         1440.55
Permanent Ineff=
       F       F
Bank Sta=515.44,524.2
XS Rating Curve= 0 ,0
Exp/Cntr(USF)=0,0
Exp/Cntr=0.3,0.1

Type RM Length L Ch R = 1 ,3017    ,167.8,169,169.9
XS GIS Cut Line= 6
2191997.75460301742995.568935534 2191634.9738325743096.511647036
2191562.71839958743116.6162656152191394.12326434743163.527589118
2191325.12938485743190.4609964422191058.00543475743128.274591443
#Sta/Elev= 30
       0 1549.34    51.3 1543.23    80.5 1530.35    88.8 1524.97   142.8 1506.12
   213.4 1493.22   242.5 1484.89   262.4 1476.36   285.2 1474.58   304.7 1463.71
   329.6 1452.98   354.6 1450.13   369.6 1445.96   391.9 1437.18   400.2 1430.52
   441.1 1431.98   458.4 1423.92   495.7 1413.89   528.3 1411.42   533.1 1410.59
  535.921411.419   541.8 1413.19   654.4 1414.21   675.9  1412.5   705.7 1413.25
     718 1410.98   812.5 1415.85   894.6 1426.75     948  1443.4   974.9 1448.15
#Mann= 8 ,-1,0
       0      .1       0  285.31     .07       0  446.56     .05       0
   528.3    .045       0  535.92     .05       0  551.56     .06       0
  750.63     .05       0  860.63      .1       0
#XS Ineff= 2 , 0
                          702.37         1440.83
Permanent Ineff=
       F       F
Bank Sta=528.3,535.92
XS Rating Curve= 0 ,0
Exp/Cntr(USF)=0,0
Exp/Cntr=0.3,0.1

Type RM Length L Ch R = 1 ,2848    ,71.3,71.1,71.1
XS GIS Cut Line= 2
2191822.18793166742930.5594873392191051.66055396743025.214790202
#Sta/Elev= 30
       0 1503.98    22.2 1502.06    50.4 1495.51    62.5  1487.7   122.6 1466.92
   139.1 1458.09   151.1 1458.17   163.2  1455.5   179.4 1453.86   195.5 1445.69
   219.7  1438.5   235.8 1426.85     260 1429.17     272 1429.87   280.1 1427.66
   284.2 1425.57   296.2 1416.81   304.3 1413.44   332.5  1412.7  339.061410.837
   344.6 1409.99  350.481410.808   356.7 1412.33   372.8 1412.87     460 1413.46
   574.3  1413.6   642.8 1416.15     663 1420.98   751.6 1449.99   776.3 1455.71
#Mann= 8 ,-1,0
       0      .1       0      60     .07       0     260     .05       0
  339.06    .045       0  350.48     .07       0     360     .05       0
     460     .06       0     550      .1       0
Bank Sta=339.06,350.48
XS Rating Curve= 0 ,0
Exp/Cntr(USF)=0,0
Exp/Cntr=0.3,0.1

Type RM Length L Ch R = 1 ,2777    ,63.9,63.6,63.6
XS GIS Cut Line= 3
2191825.38154883 742855.028412462191448.70659884742905.719508219
2190978.01487319742946.851175626
#Sta/Elev= 30
       0 1505.57    29.5 1499.97    53.7 1493.55    65.8 1487.15      94 1476.46
   114.2 1467.17   138.4 1458.67   150.6 1453.39   154.6 1452.56   178.8 1452.11
   182.8 1450.86   194.9 1444.62   219.2 1437.88   231.3 1432.63   243.4 1425.87
   279.7 1427.95   287.8 1425.91   295.8 1421.13   303.9 1417.93   336.2  1414.1
346.36251411.108   352.4 1410.24  357.071411.128   368.5 1413.39   601.6 1414.44
   653.6 1417.02   677.7 1421.69   750.8 1440.76   804.7 1455.66   852.6 1471.03
#Mann= 6 ,-1,0
       0      .1       0      60     .07       0     260     .05       0
346.3625    .045       0  357.07     .05       0  660.07      .1       0
Bank Sta=346.3625,357.07
XS Rating Curve= 0 ,0
Exp/Cntr(USF)=0,0
Exp/Cntr=0.3,0.1

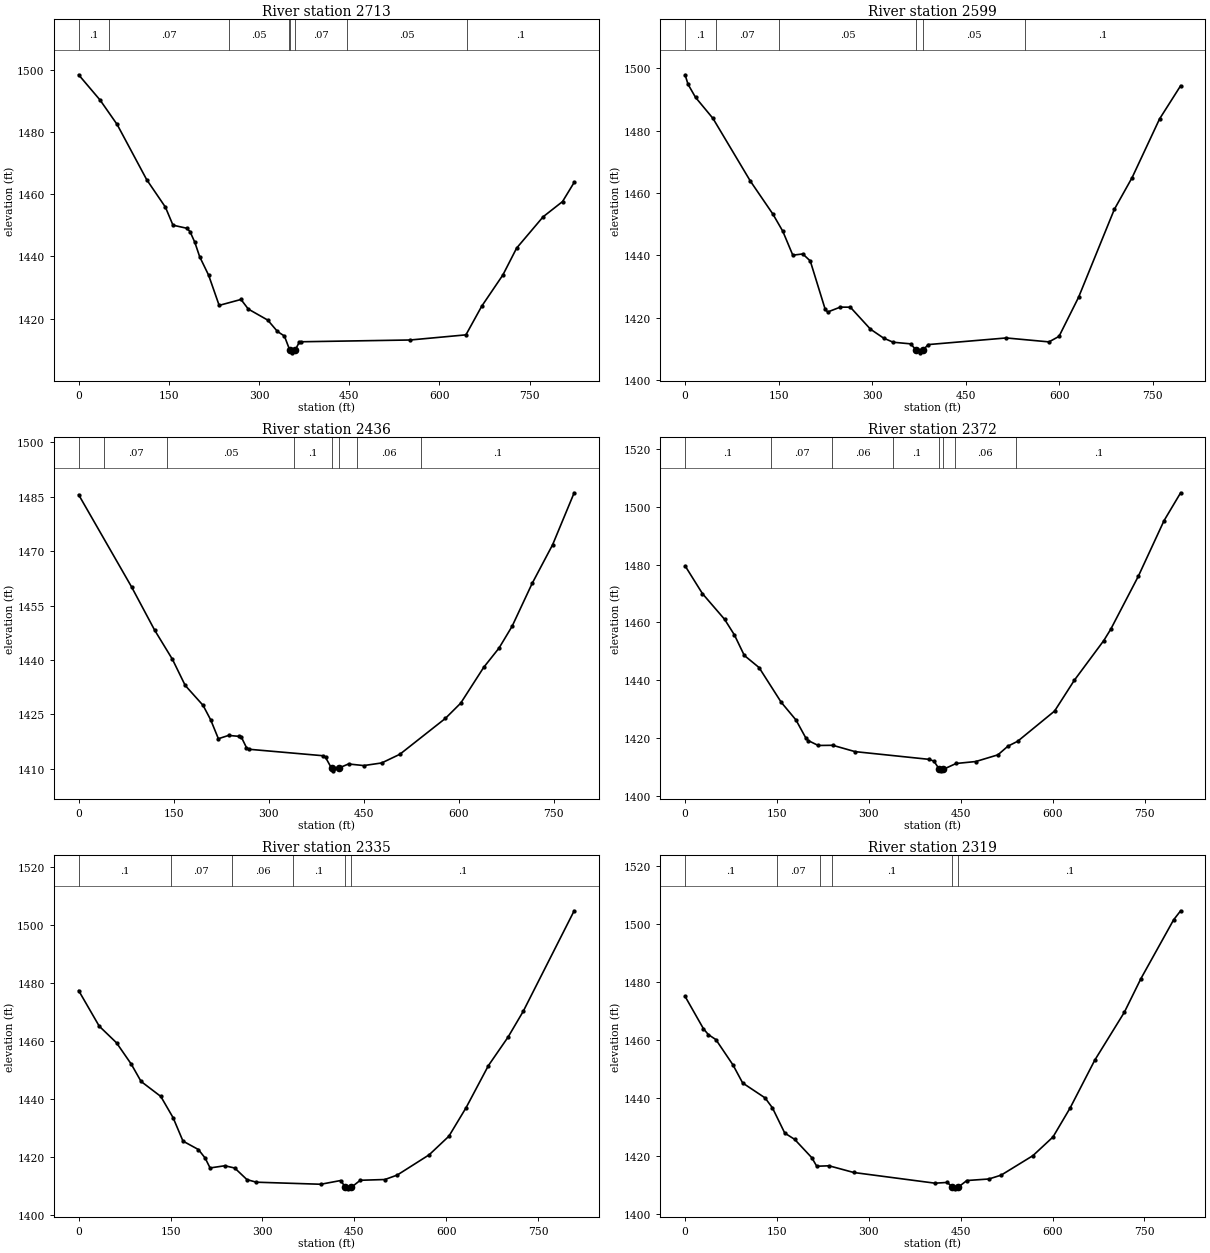
Type RM Length L Ch R = 1 ,2713    ,111.4,114.3,117
XS GIS Cut Line= 3
2191815.47436359742789.0664982572191443.07211951742842.613339754
2190996.84353252 742880.32581349
#Sta/Elev= 30
       0 1498.38    35.7 1490.25      64 1482.42   113.2 1464.67   144.3 1455.85
   156.9 1450.05   179.7 1449.07   185.2 1448.01   193.3 1444.51   201.3 1439.91
   216.2 1433.97   233.7 1424.28     270 1426.18   282.2 1423.09   314.5 1419.55
   330.7 1415.89   342.2 1414.43   350.9 1410.02   354.9 1409.03  360.111409.943
   366.9 1412.42   370.5 1412.59   551.6 1413.16   644.1 1414.81   670.4 1424.03
   705.5 1434.04   728.4 1442.69   772.5 1452.75   804.7 1457.63   824.1  1463.8
#Mann= 8 ,-1,0
       0      .1       0      50     .07       0     250     .05       0
     350     .07       0   350.9    .045       0  360.11     .07       0
  446.23     .05       0  646.23      .1       0
Bank Sta=350.9,360.11
XS Rating Curve= 0 ,0
Exp/Cntr(USF)=0,0
Exp/Cntr=0.3,0.1

Type RM Length L Ch R = 1 ,2599    ,163.3,163.4,163.6
XS GIS Cut Line= 3
2191812.86972868742755.190639082 2191587.4905556742748.234491764
2191022.65139341 742675.19494493
#Sta/Elev= 30
       0  1497.9     4.7 1494.85    16.7 1490.67    44.7 1483.92   104.7 1463.83
   140.8 1453.27   156.8 1447.73   172.8 1440.09   188.8 1440.48   200.8 1438.24
   224.8 1422.71   228.8 1421.88   248.9 1423.44   265.1 1423.42   297.4 1416.37
   318.4 1413.52   333.7 1412.19   361.9 1411.67  370.981409.597   377.6 1408.79
  381.121409.615   390.2 1411.44   515.2 1413.56   583.8  1412.3   599.9 1414.07
   631.2 1426.57   688.6 1454.76   717.2 1464.97   761.2 1483.76     795 1494.39
#Mann= 6 ,-1,0
       0      .1       0      50     .07       0     150     .05       0
  370.98    .045       0  381.12     .05       0  545.49      .1       0
Bank Sta=370.98,381.12
XS Rating Curve= 0 ,0
Exp/Cntr(USF)=0,0
Exp/Cntr=0.3,0.1

Type RM Length L Ch R = 1 ,2436    ,64.4,63.9,62.6
XS GIS Cut Line= 2
2191807.30481083742618.1545369272191030.30315546742524.942162872
#Sta/Elev= 30
       0  1485.5    83.7 1460.09     120 1448.23   148.2 1440.17   168.3    1433
   196.5 1427.52   208.6 1423.51   220.7 1418.33   236.8 1419.24   252.9 1418.99
     257 1418.76     265 1415.91     269 1415.43   385.9 1413.65   389.9  1413.2
   399.4 1410.22     402 1409.49  411.191410.274   426.2 1411.38   450.3 1410.94
   478.6 1411.66   507.3 1414.05   579.1 1423.91   603.4 1428.12   639.7 1437.97
   663.9 1443.28   684.6 1449.29   716.2 1461.07   748.5 1471.71   782.6 1486.03
#Mann= 8 ,-1,0
       0      .1       0      40     .07       0     140     .05       0
     340      .1       0   399.4    .045       0  411.19      .1       0
     440     .06       0     540      .1       0
Bank Sta=399.4,411.19
XS Rating Curve= 0 ,0
Exp/Cntr(USF)=0,0
Exp/Cntr=0.3,0.1

Type RM Length L Ch R = 1 ,2372    ,36.4,37,38.1
XS GIS Cut Line= 3
2191808.33409082742548.088952116 2191154.6146781742484.896075553
2191003.16968082742472.911219653
#Sta/Elev= 30
       0 1479.57    28.3 1469.97    64.5 1461.07    80.5 1455.68    96.6  1448.6
   120.7 1444.41   156.9 1432.39     181 1426.27     197 1420.07   201.1 1419.15
   217.2 1417.47     241 1417.53   277.4 1415.34   397.3 1412.69   405.9 1412.09
   415.1 1409.21   418.1  1408.7   421.51409.226   442.2 1411.24   474.4 1411.92
   510.5 1414.23   526.8 1417.22   542.7 1418.92     603 1429.37   635.1 1439.98
   683.3 1453.75   694.6 1457.64   739.5 1475.91   781.7 1495.23   808.7 1504.83
#Mann= 8 ,-1,0
       0      .1       0     140     .07       0     240     .06       0
     340      .1       0   415.1    .045       0   421.5      .1       0
     440     .06       0     540      .1       0
Bank Sta=415.1,421.5
XS Rating Curve= 0 ,0
Exp/Cntr(USF)=0,0
Exp/Cntr=0.3,0.1

Type RM Length L Ch R = 1 ,2335    ,16.7,16.4,15.5
XS GIS Cut Line= 3
2191813.64649312742517.069138966 2191159.9270804742453.876262403
2191008.48208312742441.891406503
#Sta/Elev= 30
       0 1477.37    33.6  1465.1    61.8 1459.38    85.9 1452.02   101.9 1446.06
   134.1 1440.89   154.2 1433.56   170.3 1425.51   195.5  1422.6   206.4 1419.69
   214.5 1416.27   238.6 1417.02   254.7 1416.24   274.7 1412.25   289.9 1411.36
   395.3 1410.65   427.5 1411.93   435.5 1409.61   439.5 1409.07  445.141409.612
   459.6 1412.02   499.8 1412.28   519.9 1413.81   572.1  1420.8   604.3 1427.21
   632.4 1437.06   668.8 1451.54   700.7  1461.3   725.5 1470.19   808.7 1504.84
#Mann= 6 ,-1,0
       0      .1       0     150     .07       0     250     .06       0
     350      .1       0   435.5    .045       0  445.14      .1       0
Bank Sta=435.5,445.14
XS Rating Curve= 0 ,0
Exp/Cntr(USF)=0,0
Exp/Cntr=0.3,0.1

Type RM Length L Ch R = 1 ,2319    ,28.2,27.9,27.2
XS GIS Cut Line= 4
 2191809.9835842742502.5166966232191396.72953983742459.918344036
2191281.07561572742456.694484981 2191004.8191742742427.338964161
#Sta/Elev= 30
       0 1475.15      30 1463.99      38 1461.97    50.3 1460.25    78.2  1451.5
      94 1445.28   130.5 1440.15   142.6  1436.7   162.7    1428   178.8 1425.84
   206.9 1419.49   214.9 1416.56     235 1416.71   275.3  1414.4     408 1410.71
     428 1410.97     436 1409.42     440 1408.76   446.1 1409.38     460 1411.63
     496 1412.16     516 1413.49   567.9 1420.22   600.6 1426.65   628.6 1436.67
   668.8 1453.15     717 1469.65   744.2 1481.31   797.5 1501.57     809  1504.7
#Mann= 6 ,-1,0
       0      .1       0     150     .07       0     220     .08       0
     240      .1       0     436    .045       0   446.1      .1       0
Bank Sta=436,446.1
XS Rating Curve= 0 ,0
Exp/Cntr(USF)=0,0
Exp/Cntr=0.3,0.1

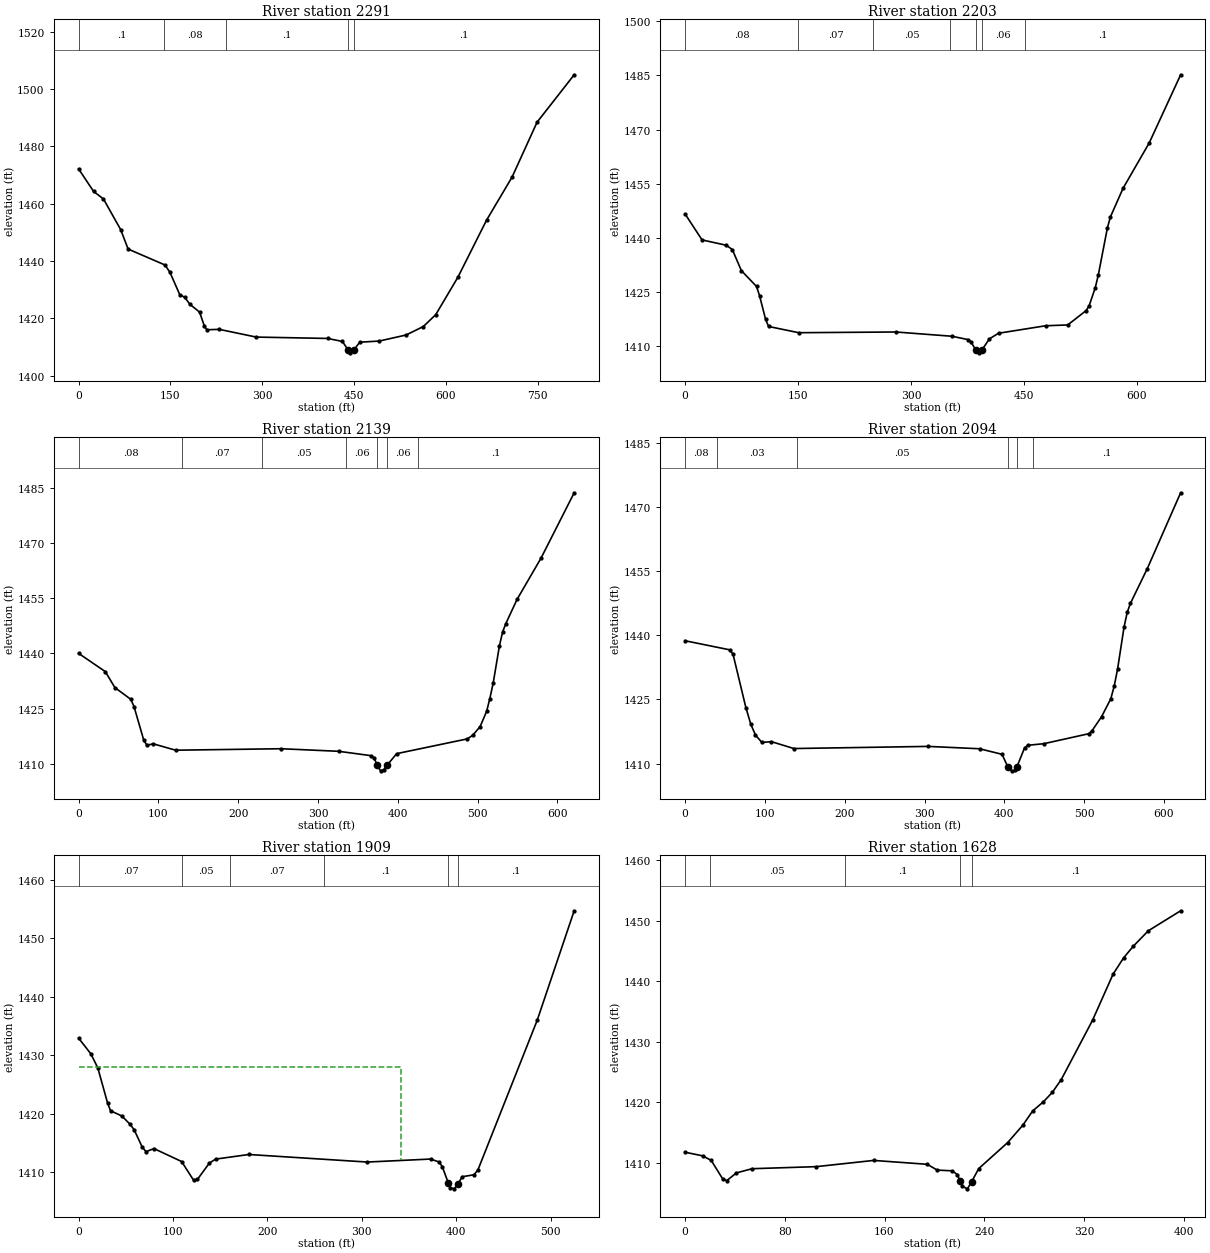
Type RM Length L Ch R = 1 ,2291    ,90.5,87.8,85.3
XS GIS Cut Line= 4
2191804.44429303 742478.614886152191390.82057048742433.059108053
2191275.53632456742432.7926745082190999.27988303742403.437153687
#Sta/Elev= 30
       0 1472.16    24.4 1464.32    40.5  1461.7    68.7 1450.97    80.8 1444.21
   141.1 1438.64   149.2 1436.04   165.3 1428.22   173.3  1427.4   181.4 1424.99
   197.5 1422.21   205.5 1417.21   209.5 1416.06   229.6 1416.19     290  1413.5
   406.7 1413.02   430.8 1411.97  440.131408.955   442.8    1408449.20331408.922
     459 1411.71   490.8 1412.11   534.8 1414.23   562.9 1417.18   583.1 1421.31
   619.3 1434.37   666.1 1454.28   707.8 1469.32   748.6 1488.46   809.2 1505.01
#Mann= 5 ,-1,0
       0      .1       0     140     .08       0     240      .1       0
  440.13    .045       0449.2033      .1       0
Bank Sta=440.13,449.2033
XS Rating Curve= 0 ,0
Exp/Cntr(USF)=0,0
Exp/Cntr=0.3,0.1

Type RM Length L Ch R = 1 ,2203    ,62.5,64.3,65.9
XS GIS Cut Line= 5
2191718.65397234742337.8721713712191454.30267498742317.532648544
2191409.85577405742329.3403500162191198.37563231742386.721439351
2191071.64122883742371.206498623
#Sta/Elev= 30
       0 1446.65    22.5 1439.48    54.6    1438    62.7 1436.81    74.7 1430.98
    94.8  1426.6    98.8 1424.09   106.8 1417.55   110.8 1415.53   150.9  1413.8
   279.8    1414   354.3 1412.82     375 1411.92   379.2 1411.33386.34791408.927
   390.6 1408.23393.83731408.941     404  1412.1   416.1 1413.65   478.5 1415.72
     508 1415.95   532.5 1419.93   536.5 1421.31   544.6 1426.28   548.6 1429.78
   560.7 1442.85   564.7 1445.86   581.5 1453.78   616.2 1466.32   657.9 1485.17
#Mann= 7 ,-1,0
       0     .08       0     150     .07       0     250     .05       0
  351.12     .06       0386.3479    .045       0393.8373     .06       0
  451.12      .1       0
Bank Sta=386.3479,393.8373
XS Rating Curve= 0 ,0
Exp/Cntr(USF)=0,0
Exp/Cntr=0.3,0.1

Type RM Length L Ch R = 1 ,2139    ,44.6,44.4,44.5
XS GIS Cut Line= 4
2191693.50112479742301.7195408082191368.64506843742282.657082733
2191187.55171672742304.1023480672191074.76550644742312.839308018
#Sta/Elev= 30
       0    1440    33.4 1435.06    45.4 1430.73    65.4 1427.53    69.4 1425.57
    81.5 1416.53    85.5 1415.07    93.5 1415.46   121.5 1413.73   253.8 1414.13
   325.9 1413.43   366.2 1412.25   370.2 1411.65   374.2 1409.62   378.3 1408.13
   382.3 1408.44   386.3 1409.59   398.4 1412.79     487  1416.8   493.8 1417.78
   503.1 1420.16   511.2 1424.27   515.2 1427.72   519.4 1431.91   527.2 1441.98
   531.2  1445.8   535.2 1448.06   549.4 1454.68   579.4 1465.86   620.9 1483.58
#Mann= 7 ,-1,0
       0     .08       0     130     .07       0     230     .05       0
  335.41     .06       0   374.2    .045       0   386.3     .06       0
  425.41      .1       0
Bank Sta=374.2,386.3
XS Rating Curve= 0 ,0
Exp/Cntr(USF)=0,0
Exp/Cntr=0.3,0.1

Type RM Length L Ch R = 1 ,2094    ,186.7,185,182.7
XS GIS Cut Line= 4
2191708.19510289742256.2502013832191383.33904653742237.187743308
2191202.24569482742258.6330086422191089.45948454742267.369968593
#Sta/Elev= 30
       0 1438.75    56.1 1436.62    60.1 1435.57    76.2 1423.06    82.4 1419.17
    88.2 1416.67    96.2 1414.95   108.2 1415.13   136.3 1413.52   304.5 1414.02
   368.9 1413.47   397.1 1412.17  404.221409.301   409.2  1408.3   413.2 1408.38
   415.9  1409.3   425.3 1413.66   429.3 1414.28   449.4 1414.65   505.8 1416.99
   509.9 1417.69   521.9    1421   533.4 1425.17   537.7 1428.16   541.9 1432.14
     550 1441.96     554 1445.43     558 1447.51   579.1 1455.63   620.9 1473.39
#Mann= 6 ,-1,0
       0     .08       0      40     .03       0     140     .05       0
  404.22    .045       0   415.9     .05       0  435.41      .1       0
Bank Sta=404.22,415.9
XS Rating Curve= 0 ,0
Exp/Cntr(USF)=0,0
Exp/Cntr=0.3,0.1

Type RM Length L Ch R = 1 ,1909    ,276.5,280.9,284.4
XS GIS Cut Line= 2
 2191620.4644061741956.1363889412191118.69645637742110.540387806
#Sta/Elev= 30
       0 1432.94    12.9 1430.28    20.3 1427.87    30.7 1421.84    33.8 1420.54
    45.9 1419.63    54.7 1418.19    58.9 1417.27    67.3 1414.34    71.4 1413.54
    79.8 1414.07   109.1 1411.86   121.7 1408.68   125.9 1408.81   138.4 1411.57
   145.1 1412.27   180.3 1413.06   305.8 1411.77   372.8 1412.28   381.9 1411.78
   385.3 1410.97   391.8 1408.12   393.7 1407.37   397.9 1407.19   402.1 1408.06
   406.3 1409.26   418.8 1409.59     423 1410.41   485.8 1435.99     525 1454.72
#Mann= 6 ,-1,0
       0     .07       0     110     .05       0     160     .07       0
     260      .1       0   391.8    .045       0   402.1      .1       0
#XS Ineff= 2 , 0
          341.91 1428.09
Permanent Ineff=
       F       F
Bank Sta=391.8,402.1
XS Rating Curve= 0 ,0
Exp/Cntr(USF)=0,0
Exp/Cntr=0.3,0.1

Type RM Length L Ch R = 1 ,1628    ,147.5,148.1,148.6
XS GIS Cut Line= 3
2191385.99290543741771.8086102282191293.75318334741828.000624834
2191006.43175017741791.952917351
#Sta/Elev= 30
       0 1411.72      14 1411.12    20.9 1410.38    30.2 1407.29    33.4 1407.01
    41.1 1408.29    53.7 1408.99   105.2 1409.33   151.3 1410.36   194.3 1409.72
   202.3 1408.76   214.4 1408.64   218.4 1408.02  220.781406.894   222.5 1406.08
   226.5 1405.66   229.81406.799   235.6 1409.01   258.8 1413.31   270.9 1416.17
   278.9 1418.55   287.5 1420.06   294.6 1421.61   301.8 1423.73   326.9 1433.54
   343.4 1441.18   351.9 1443.89   359.5 1445.77   371.6 1448.34   397.6 1451.66
#Mann= 5 ,-1,0
       0     .06       0      20     .05       0  128.01      .1       0
  220.78    .045       0   229.8      .1       0
Bank Sta=220.78,229.8
XS Rating Curve= 0 ,0
Exp/Cntr(USF)=0,0
Exp/Cntr=0.3,0.1

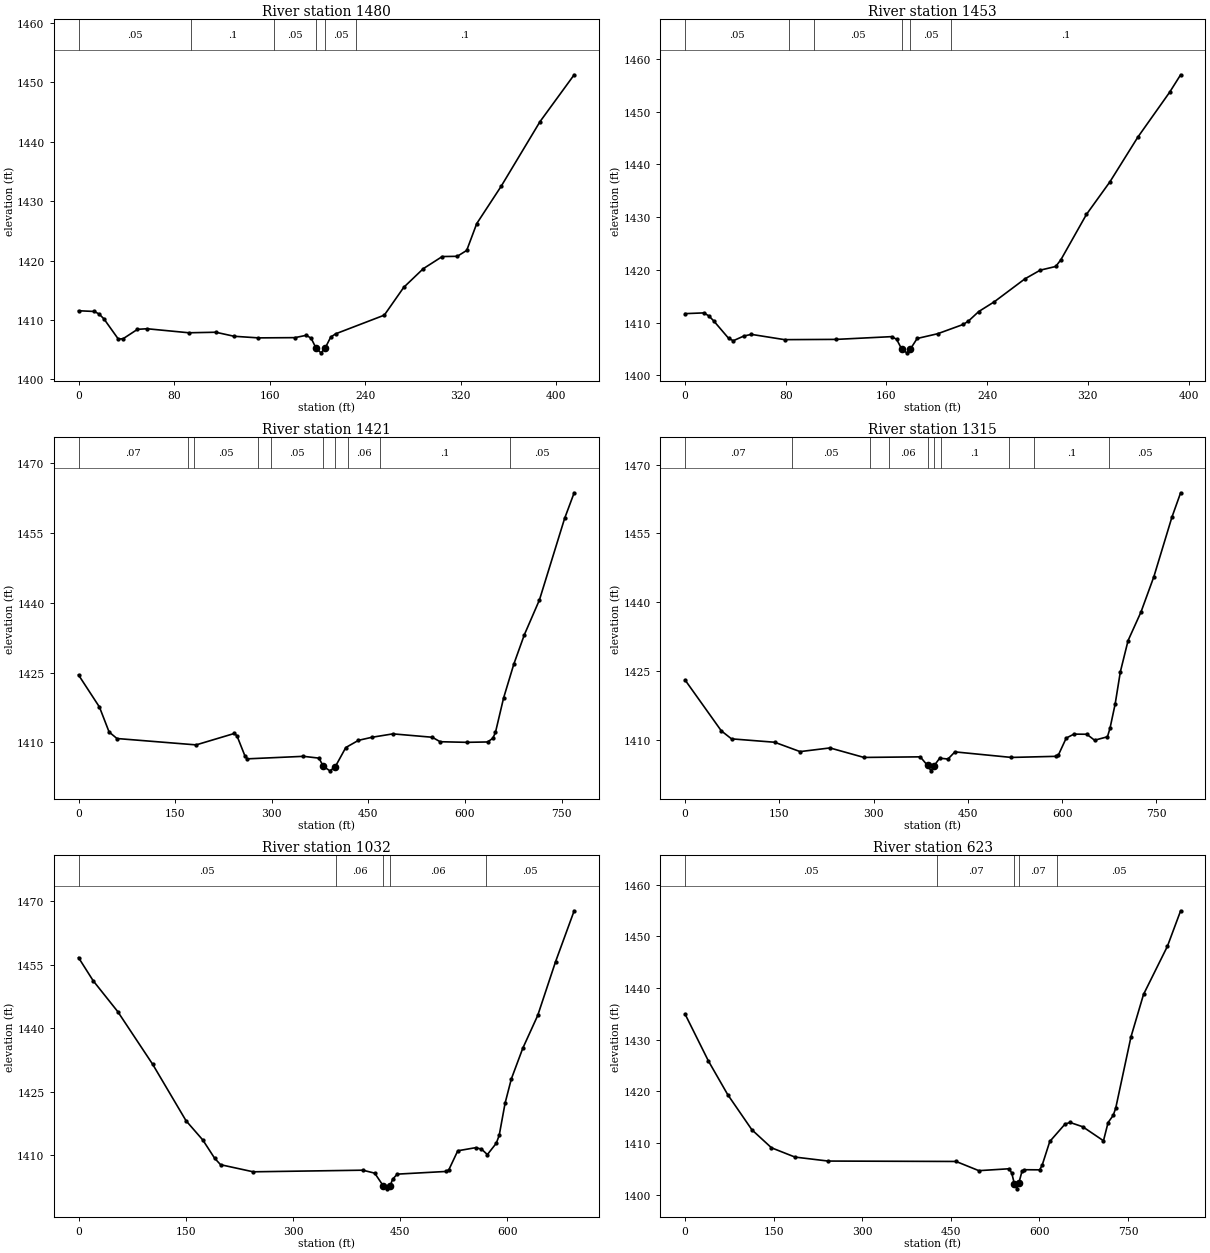
Type RM Length L Ch R = 1 ,1480    ,27.6,27.7,27.7
XS GIS Cut Line= 4
2191361.41043923741751.7843370942191287.52324116741757.329322686
2191220.53811884741672.3097443612190992.10167607741627.652996149
#Sta/Elev= 30
       0 1411.54    13.3 1411.42    17.3 1410.98    21.3 1410.17    33.3 1406.78
    37.3 1406.82    49.4 1408.41    57.4 1408.51    92.4 1407.83     115 1407.92
   130.3 1407.24   150.6 1406.97   181.2 1407.01   190.9 1407.41   194.9 1406.88
     199 1405.21   203.1 1404.45  206.541405.241   211.2  1407.1   215.3 1407.65
   256.1  1410.8   272.4 1415.49   288.7 1418.62   304.6 1420.67   317.2 1420.71
   325.1  1421.7   333.5 1426.22   353.9 1432.49   386.5  1443.4   415.1 1451.29
#Mann= 6 ,-1,0
       0     .05       0   94.09      .1       0  164.09     .05       0
     199    .045       0  206.54     .05       0  232.33      .1       0
Bank Sta=199,206.54
XS Rating Curve= 0 ,0
Exp/Cntr(USF)=0,0
Exp/Cntr=0.3,0.1

Type RM Length L Ch R = 1 ,1453    ,17.9,31.9,46.2
XS GIS Cut Line= 4
2191342.90080277741728.5810442032191290.21813851741729.885123032
2191223.23301619741644.8655447072190994.79657342741600.208796495
#Sta/Elev= 30
       0 1411.69      15 1411.83    18.9 1411.27    22.7 1410.35    34.7    1407
    38.4 1406.56    46.7 1407.44    52.7 1407.76    79.1 1406.76   120.2 1406.81
   164.1 1407.33   168.1 1406.83   172.2 1404.95   176.3 1404.26  178.961404.948
   184.4 1406.98   200.7 1407.88   221.1 1409.65   225.2 1410.29   233.3 1412.08
   245.6 1413.92     270 1418.28   282.2 1419.93   294.5 1420.63   298.6 1421.91
   318.9  1430.5   337.5 1436.66   359.7 1445.14   384.9 1453.63   393.7 1456.96
#Mann= 6 ,-1,0
       0     .05       0    82.7      .1       0   102.7     .05       0
   172.2    .045       0  178.96     .05       0  210.94      .1       0
Bank Sta=172.2,178.96
XS Rating Curve= 0 ,0
Exp/Cntr(USF)=0,0
Exp/Cntr=0.3,0.1

Type RM Length L Ch R = 1 ,1421    ,110.5,105.5,100.4
XS GIS Cut Line= 6
2191547.09862315 741666.905045182191281.44226374741709.460420608
2191232.91085993741647.3931310722191165.35985395741526.455039718
2191109.79370387741394.621624819 2190972.5126272741422.949466037
#Sta/Elev= 30
       0 1424.52    32.5 1417.62    47.5 1412.25    59.7 1410.85   182.6 1409.48
     242 1411.94     246 1411.44   258.2 1407.18   262.2 1406.48   349.3 1407.02
   373.5 1406.63  379.831404.898   390.4  1403.9   398.6 1404.77     415 1408.91
   434.7 1410.46   455.7 1411.12   488.2 1411.85   549.3 1411.12   561.5 1410.16
   602.7 1410.03   635.2 1410.11   643.3 1410.91   647.4 1412.17     660 1419.56
     676 1426.89   692.3 1433.18   715.7 1440.66   754.8 1458.19   769.6 1463.69
#Mann= 10 ,-1,0
       0     .07       0     170     .06       0     180     .05       0
  279.04      .1       0  299.04     .05       0  379.83    .045       0
   398.6     .05       0  417.83     .06       0  467.83      .1       0
  669.42     .05       0
Bank Sta=379.83,398.6
XS Rating Curve= 0 ,0
Exp/Cntr(USF)=0,0
Exp/Cntr=0.3,0.1

Type RM Length L Ch R = 1 ,1315    ,294.8,282.9,268.5
XS GIS Cut Line= 6
2191541.37981297741636.0512006422191338.68140046741665.111671744
2191287.14687842741592.6849767422191233.23495899741504.863531126
  2191164.942508741329.4164355042190966.64761948 741374.08726204
#Sta/Elev= 30
       0  1423.1    57.8 1411.99      74 1410.25   142.6 1409.51   183.1 1407.47
   230.6 1408.27   284.7  1406.2   374.2 1406.33   385.8 1404.46   391.4 1403.28
   396.4 1404.43   405.2 1406.04   418.3 1405.85   429.4 1407.41   519.3  1406.2
     590 1406.44   594.1 1406.77   606.4 1410.42   618.7 1411.28   639.2 1411.25
   651.5 1409.95     672  1410.7   676.1 1412.59   684.3 1417.87   692.5 1424.85
   704.8 1431.66   725.3 1437.87   745.8 1445.57   774.5 1458.53   788.4 1463.86
#Mann= 10 ,-1,0
       0     .07       0     170     .05       0  293.75     .07       0
  323.75     .06       0   385.8    .045       0   396.4     .06       0
  406.82      .1       0  515.45     .06       0  555.45      .1       0
  675.13     .05       0
Bank Sta=385.8,396.4
XS Rating Curve= 0 ,0
Exp/Cntr(USF)=0,0
Exp/Cntr=0.3,0.1

Type RM Length L Ch R = 1 ,1032    ,409.7,409.3,407.6
XS GIS Cut Line= 2
2191623.92175053741121.6454890252190955.02473138741303.898457152
#Sta/Elev= 30
       0 1456.65    20.5 1451.19    54.8 1443.92   103.7 1431.48   150.4 1418.15
   173.9  1413.6   190.4  1409.3   198.7 1407.78   244.3  1406.1   397.7 1406.48
   414.3 1405.78   426.2  1402.8   430.9 1402.08     436 1402.79   439.2 1404.31
   445.8 1405.55   513.8 1406.18     518 1406.58   530.5 1411.06   555.3 1411.79
   563.6 1411.47   571.9 1410.16   584.3 1412.83   588.4 1414.67   596.7 1422.32
   605.4 1428.01   621.4 1435.25   642.3 1442.99   667.2 1455.65   693.3  1467.7
#Mann= 5 ,-1,0
       0     .05       0     360     .06       0   426.2    .045       0
     436     .06       0     570     .05       0
Bank Sta=426.2,436
XS Rating Curve= 0 ,0
Exp/Cntr(USF)=0,0
Exp/Cntr=0.3,0.1

Type RM Length L Ch R = 1 ,623     ,224.1,226.4,228.2
XS GIS Cut Line= 4
2191594.98348653740880.3097226782191451.82178102740849.517246883
2191139.18610755740826.7964463462190785.61055501740963.658475026
#Sta/Elev= 30
       0 1435.01    39.7 1425.89    72.4 1419.37   113.3 1412.57   146.4 1409.09
   186.2 1407.29   242.3 1406.52   458.9 1406.44   497.4 1404.66   548.9 1405.03
   553.2 1404.16   557.5 1402.13   561.8 1401.14  565.11 1402.27   570.4  1404.5
   574.6 1404.84   600.4 1404.82   604.7 1405.75   617.5 1410.31   643.4 1413.69
   651.9 1413.99   673.3 1413.16   708.4 1410.45   716.2 1413.98   724.8 1415.35
   729.1 1416.76   754.9 1430.55   776.2 1438.79   816.6  1448.1     839 1454.98
#Mann= 5 ,-1,0
       0     .05       0  426.44     .07       0   557.5    .045       0
  565.11     .07       0   629.9     .05       0
Bank Sta=557.5,565.11
XS Rating Curve= 0 ,0
Exp/Cntr(USF)=0,0
Exp/Cntr=0.3,0.1

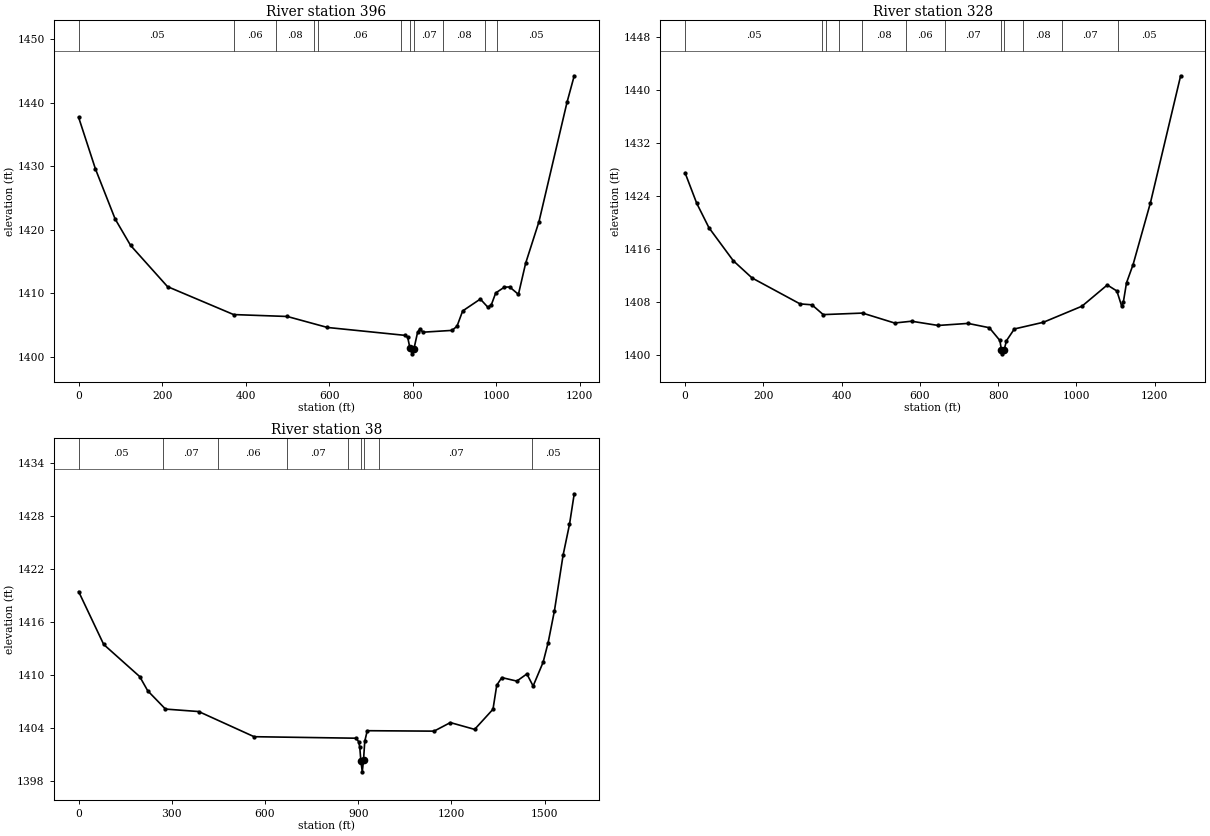
Type RM Length L Ch R = 1 ,396     ,69.1,68.6,67.4
XS GIS Cut Line= 4
2191629.68280303740832.6626859052191380.01881376 740568.83477603
2190763.55288992740699.6347913282190706.37976188740884.910771565
#Sta/Elev= 30
       0 1437.68    40.3 1429.56    87.4  1421.7   124.4 1417.54   212.9 1411.05
   371.3 1406.65   499.8 1406.35   596.1 1404.62   781.7 1403.38   788.3 1403.08
  793.841401.321   798.5 1400.47  803.411401.296     812 1403.85     817 1404.33
   825.5 1403.88   894.6 1404.16   906.5 1404.82     920 1407.22   962.3 1409.09
   980.5  1407.8   988.7 1408.19   999.2 1410.05  1019.8 1410.96  1032.5    1411
  1053.6 1409.83  1070.9 1414.73  1102.9 1421.29  1170.1 1440.08  1187.3 1444.23
#Mann= 11 ,-1,0
       0     .05       0  373.23     .06       0  473.23     .08       0
  563.23     .05       0  573.23     .06       0  773.23     .07       0
  793.84    .045       0  803.41     .07       0  873.23     .08       0
  973.23     .07       0 1003.42     .05       0
Bank Sta=793.84,803.41
XS Rating Curve= 0 ,0
Exp/Cntr(USF)=0,0
Exp/Cntr=0.3,0.1

Type RM Length L Ch R = 1 ,328     ,289.5,289.5,289.5
XS GIS Cut Line= 4
 2191614.1208948740769.5595515742191364.45690553  740505.7316417
2190707.42273053740646.6737197872190659.26476942 740872.51795118
#Sta/Elev= 30
       0 1427.47    29.9 1422.85    61.1 1419.16   123.3 1414.17   171.2 1411.57
   293.8 1407.65   324.2 1407.51     353 1406.03   453.5 1406.26   535.3 1404.76
   578.6 1405.03   646.7 1404.39   722.9  1404.7   777.3 1404.05   804.3 1402.12
  808.381400.672     811  1400.1  815.161400.679   821.1 1402.08   841.3 1403.86
   915.4 1404.87    1014  1407.3  1078.7 1410.51  1103.2  1409.6  1115.5 1407.31
  1119.6 1407.87  1127.8 1410.83  1144.6 1413.59  1189.1 1422.97  1266.1 1442.13
#Mann= 12 ,-1,0
       0     .05       0     350     .06       0     360     .07       0
  393.23     .06       0  453.23     .08       0  563.23     .06       0
  663.23     .07       0  808.38    .045       0  815.16     .07       0
  863.23     .08       0  963.23     .07       0 1105.21     .05       0
Bank Sta=808.38,815.16
XS Rating Curve= 0 ,0
Exp/Cntr(USF)=0,0
Exp/Cntr=0.3,0.1

Type RM Length L Ch R = 1 ,38      ,,,
XS GIS Cut Line= 5
2191638.97893134740661.9115485772191132.64008034740318.943588519
 2190976.4670107740332.932030866 2190644.6574696740354.389447007
 2190579.0527546740844.374662176
#Sta/Elev= 30
       0 1419.43    80.7 1413.44   196.6  1409.8   222.4 1408.19   279.5 1406.12
   386.5 1405.84   564.8 1402.99   892.9 1402.82   901.3 1402.43   904.9 1401.79
  908.451400.255     913 1399.01     917 1400.37     921 1402.48     929 1403.67
    1144 1403.62  1196.5 1404.59  1274.6 1403.82  1333.7  1406.1  1345.8 1408.82
    1362 1409.69  1410.4 1409.29  1442.7  1410.1  1462.9 1408.73    1495 1411.42
  1511.3 1413.66  1531.5 1417.26  1559.3 1423.55  1579.9 1427.03  1595.2 1430.51
#Mann= 9 ,-1,0
       0     .05       0     270     .07       0     450     .06       0
  671.56     .07       0  868.36     .08       0  908.45    .045       0
     917     .08       0  968.36     .07       0 1460.86     .05       0
Bank Sta=908.45,917
XS Rating Curve= 0 ,0
Exp/Cntr(USF)=0,0
Exp/Cntr=0.3,0.1
LCMann Table=0

Chan Stop Cuts=-1
Use User Specified Reach Order=0
Composite Channel Slope=5